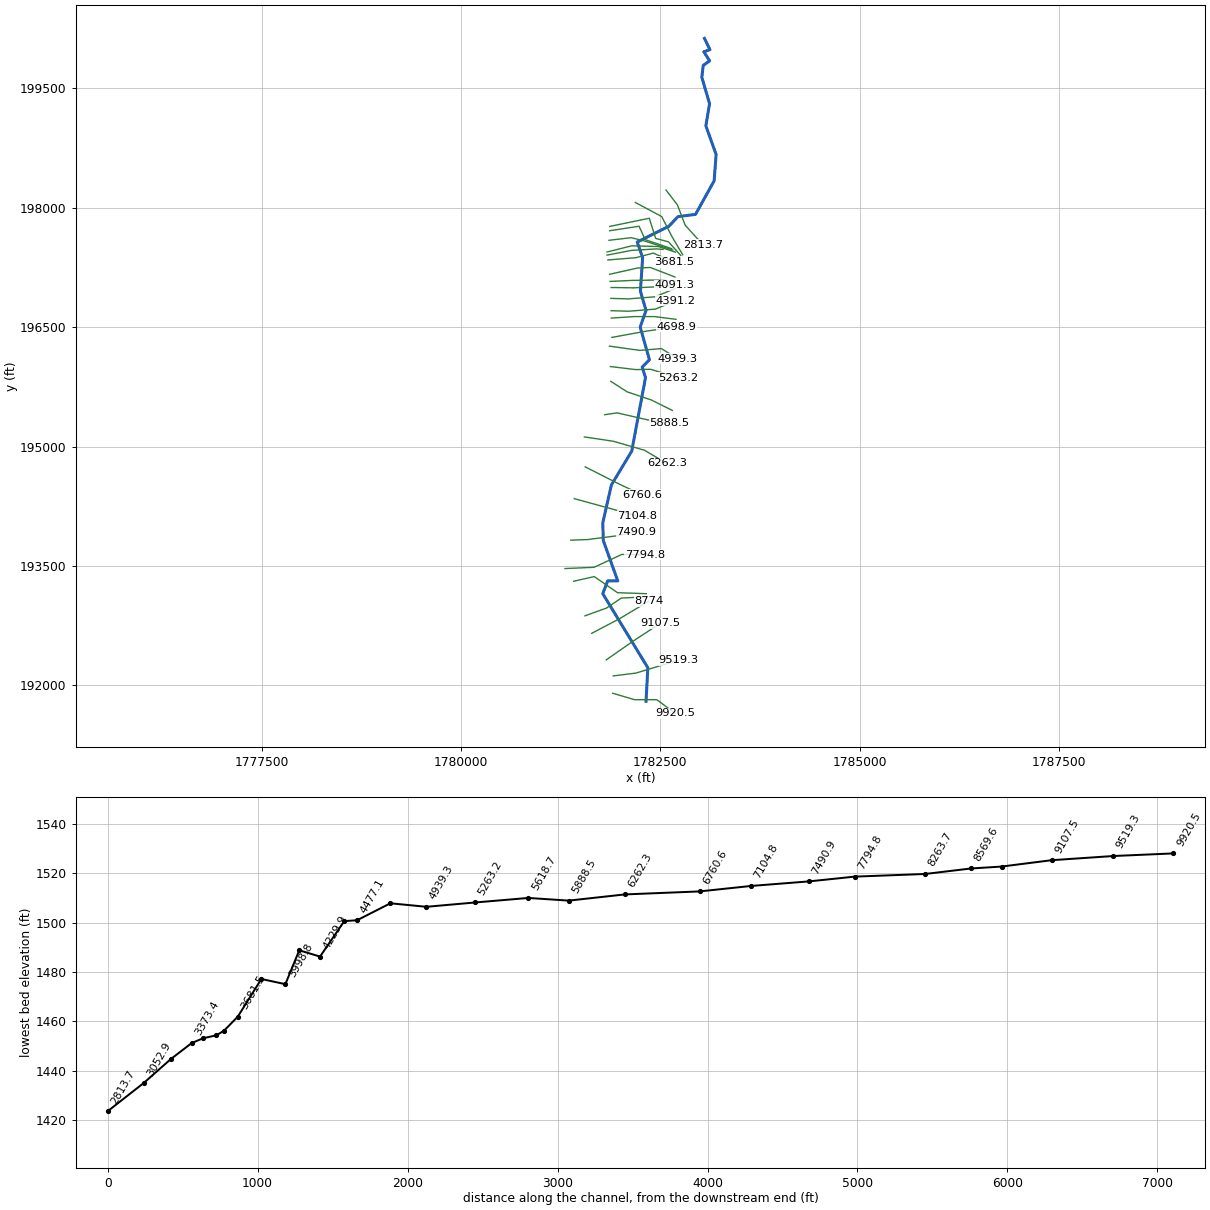
--- BrierCr.prj (project) ---

Proj Title=BrierCr
Current Plan=p01
Default Exp/Contr=0,0
English Units
Geom File=g01
Flow File=f01
Plan File=p01
BEGIN DESCRIPTION:
END DESCRIPTION:
DSS Export Rating Curves= 0
DSS Export Rating Curve Sorted= 0
DSS Export Volume Flow Curves= 0
DXF OffsetX= 0
DXF OffsetY= 0
DXF ScaleX= 0
DXF ScaleY= 0

--- BrierCr.p01 (plan) ---

Plan Title=Floodplain
Program Version=4.00
Geom File=g01
Flow File=f01
K Sum by GR=0
Std Step Tol=0.01
Critical Tol=0.01
Num of Std Step Trials=20
Max Error Tol=0.3
Flow Tol Ratio=0.001
Split Flow NTrial=30
Split Flow Tol=0.02
Split Flow Ratio=0.02
Log Output Level=0
Friction Slope Method=1
Unsteady Friction Slope Method=2
Unsteady Bridges Friction Slope Method=1
Global Log Level=0
CheckData=False
Run HTab=0
Run UNet=0
Run PostProcess=0
UNET Theta=0
UNET Theta Warmup=0
UNET ZTol=0
UNET ZSATol=0
UNET MxIter=0
UNET MaxInSteps=0
UNET DtIC=0
UNET DtMin=0
UNET MaxCRTS=0
UNET WFStab=0
UNET SFStab=0
UNET WFX=0
UNET SFX=0
UNET DSS MLevel=0
UNET DZMax Abort=0
UNET Convert EG Bridges=0
UNET Use Existing IB Tables=0
UNET Froude Limit=0
UNET Froude Power=0
Write IC File=0
Echo Input=False
Echo Output=False
Write Detailed=0

--- BrierCr.f01 (steady flow) ---

Flow Title=NFF Regression Equation
Program Version=4.00
Number of Profiles=1
Profile Names=P100yr
River Rch & RM=BrierCr,Main      ,9920.5
598.8910
River Rch & RM=BrierCr,Main      ,8569.6
637.9688
River Rch & RM=BrierCr,Main      ,8263.7
721.2969
River Rch & RM=BrierCr,Main      ,6760.6
762.5051
River Rch & RM=BrierCr,Main      ,5263.2
831.1620
River Rch & RM=BrierCr,Main      ,2147.4
911.2403
River Rch & RM=BrierCr,Main      ,1839.3
1242.150
River Rch & RM=BrierCr,Main      ,443.6
1306.870
Boundary for River Rch & Prof#=BrierCr,Main      ,1
Up Type=0
Dn Type=3
Dn Slope=0.004193

--- BrierCr.g01 (geometry) ---

Geom Title=USGS 10m DEM
Program Version=4.00

River Reach=BrierCr         ,Main
Reach XY= 30
     1782321.645      191797.284     1782344.634      192218.758
     1781779.019      193150.805     1781840.916      193310.882
     1781967.377      193310.348     1781785.422      193819.393
     1781779.553      194041.367     1781887.338      194516.795
     1782142.394      194941.533     1782315.277      195865.711
     1782273.657      195998.575     1782364.368      196090.886
     1782248.496      196501.766     1782321.645      196710.761
     1782251.283      196951.105     1782279.149      197374.669
     1782211.333      197569.974     1782609.361      197768.973
     1782721.522      197888.797      1782942.36       197917.36
     1783175.937      198338.774     1783200.818      198669.742
     1783071.937      199031.304     1783118.613      199308.571
     1783021.778      199640.177     1783039.092      199789.972
     1783120.006      199847.082      1783045.66      199961.362
     1783123.803      199987.219     1783054.266      200129.901

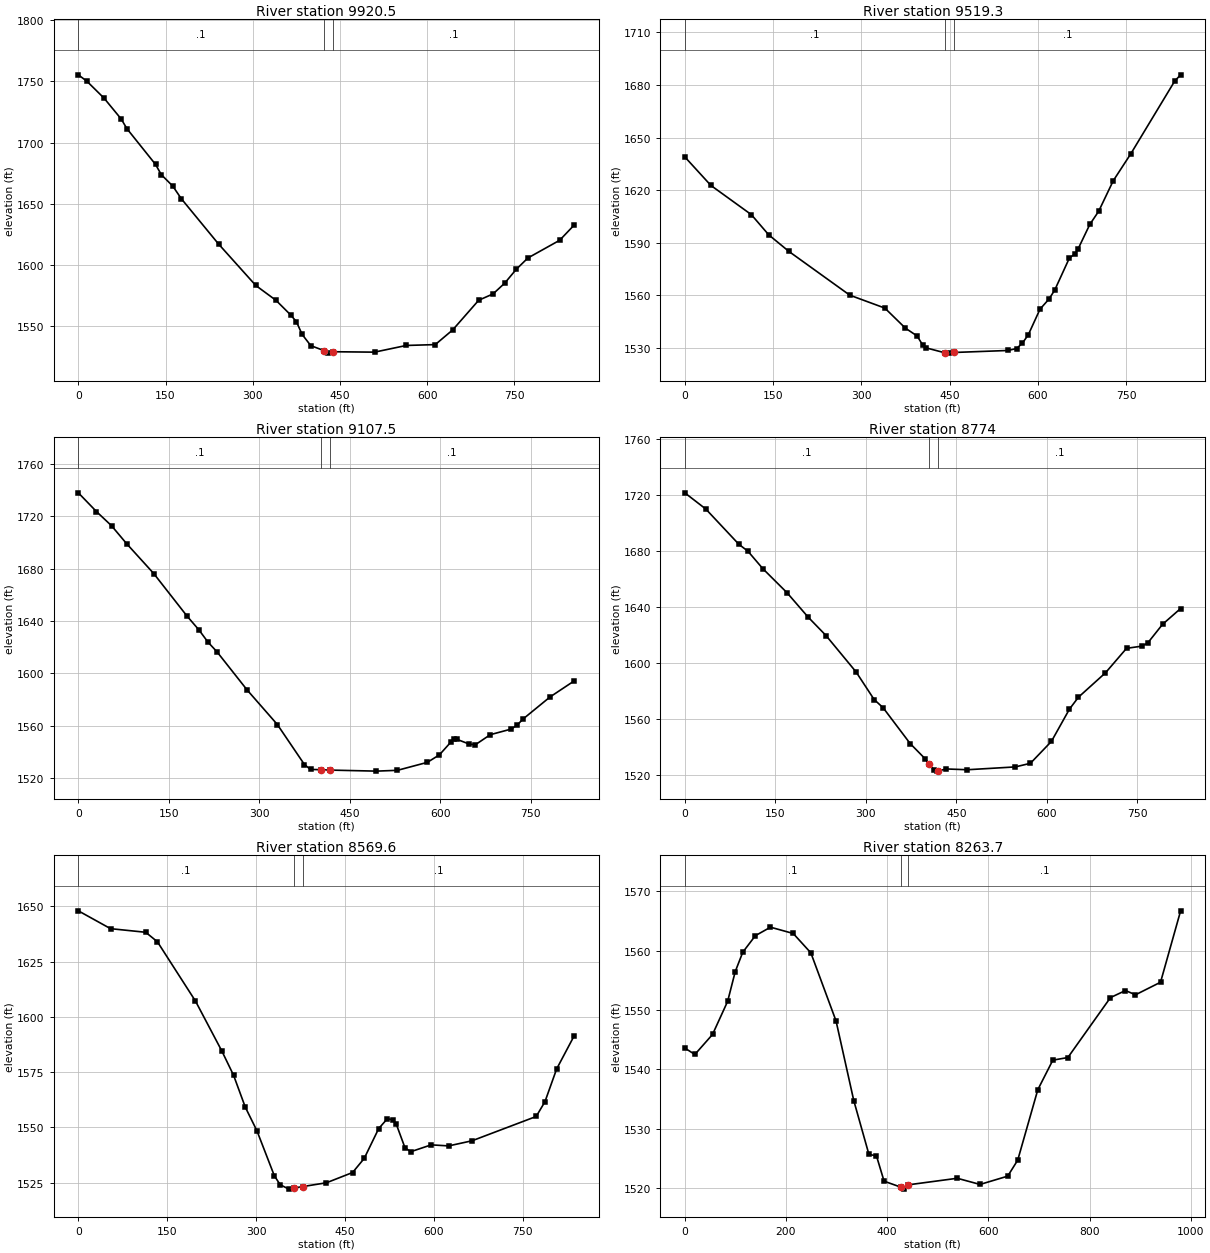
Type RM Length L Ch R = 1 ,9920.5  ,395.8,401.2,406.4
XS GIS Cut Line= 4
     1781904.515      191898.904     1782178.162      191818.066
     1782456.956      191818.066     1782688.764       191646.05
#Sta/Elev= 30
       0 1755.29    14.8 1750.03    44.3 1736.22    73.8 1719.18    83.6 1711.31
   132.8 1682.15   142.7 1673.81   162.4 1664.49   177.1 1654.19   241.1 1617.23
   305.2 1583.36   340.1 1571.18     365  1559.4     375 1553.86   384.9 1543.43
   399.8 1534.25   422.3 1530.25   429.7 1528.14   437.3 1529.28   509.4 1528.94
   564.1  1534.4   613.9  1535.1   643.8 1547.05   688.6 1571.29   713.4  1576.5
   733.4 1585.28   753.2 1596.54   773.2 1605.79   827.9 1620.26   852.8 1632.67
#Mann= 3 , 0 , 0
       0      .1       0   422.3    .045       0   437.3      .1       0
Bank Sta=422.3,437.3
XS Rating Curve= 0 ,0
Exp/Cntr=0.3,0.1

Type RM Length L Ch R = 1 ,9519.3  ,405.2,411.8,417.8
XS GIS Cut Line= 3
     1781910.446      192116.883     1782193.481      192152.005
     1782726.558      192314.379
#Sta/Elev= 30
       0 1639.03    44.3 1622.76   113.1 1606.08   142.6 1594.57     177 1585.08
   280.3 1560.15   339.9 1552.78   374.8 1541.34   394.7 1536.88   404.6 1531.53
   409.6 1530.12   442.3 1527.23   449.4 1527.08   457.3 1527.45   548.9 1528.59
   563.8 1529.69   573.8 1532.84   583.7 1537.57   603.6 1552.18   618.6 1557.84
   628.5 1562.99   653.4 1581.27   663.3 1583.85   668.3 1586.54   688.2 1600.51
   703.2 1607.98     728 1625.42   757.9 1640.83   832.5 1682.31   842.5 1685.85
#Mann= 3 , 0 , 0
       0      .1       0   442.3    .045       0   457.3      .1       0
Bank Sta=442.3,457.3
XS Rating Curve= 0 ,0
Exp/Cntr=0.3,0.1

Type RM Length L Ch R = 1 ,9107.5  ,335.3,333.5,332.5
XS GIS Cut Line= 3
     1781823.187      192318.841      1782159.32      192553.586
     1782503.653      192780.102
#Sta/Elev= 30
       0 1737.94      30 1723.66      55 1712.82      80 1699.15     125 1676.32
     180 1643.94     200 1633.23     215 1623.91     230 1616.47     280 1587.31
     330 1560.99     375 1530.38     385 1526.67   402.5 1526.48   417.5 1526.17
   494.4 1525.38   529.2    1526   578.8 1532.09   598.7  1537.8   618.6 1547.98
   623.5 1549.55   628.5 1549.54   648.4    1546   658.3 1545.52   683.1 1553.21
   717.9 1557.52   727.8 1560.64   737.7 1565.28   782.4 1582.09   822.2 1594.26
#Mann= 3 , 0 , 0
       0      .1       0   402.5    .045       0   417.5      .1       0
Bank Sta=402.5,417.5
XS Rating Curve= 0 ,0
Exp/Cntr=0.3,0.1

Type RM Length L Ch R = 1 ,8774    ,203,204.4,205.6
XS GIS Cut Line= 3
     1781640.184      192651.964     1781988.215      192835.201
     1782355.561      193055.129
#Sta/Elev= 30
       0 1721.59    34.8 1710.01    89.6 1684.82   104.6 1679.88   129.4 1667.36
   169.3 1650.27   204.1 1632.92     234 1619.63   283.8 1593.64   313.7 1573.95
   328.6 1568.07   373.4 1542.49   398.3 1531.58   404.8 1527.68   413.2 1523.68
   418.2  1522.8   419.8 1522.94   433.2 1524.35     468 1523.79   547.6 1525.81
   572.6 1528.38   607.4 1544.01   637.3 1567.09   652.2 1575.61     697 1593.03
   731.9 1610.52   756.8 1612.04   766.7 1614.18   791.6 1627.68   821.5 1638.96
#Mann= 3 , 0 , 0
       0      .1       0   404.8    .045       0   419.8      .1       0
Bank Sta=404.8,419.8
XS Rating Curve= 0 ,0
Exp/Cntr=0.3,0.1

Type RM Length L Ch R = 1 ,8569.6  ,333.7,305.9,278.2
XS GIS Cut Line= 4
     1781556.239      192871.965     1781825.841      192970.003
     1782012.725      193095.613     1782337.473      193110.931
#Sta/Elev= 30
       0 1647.96    54.4 1639.89   113.8 1638.25   133.5 1633.96   197.8 1607.12
   242.4 1584.47   262.1 1573.56   281.9 1559.12   301.6  1548.4   330.9 1528.11
   340.7 1524.05   355.4 1522.02   364.1 1522.51   379.1 1523.18     419  1524.9
   463.1 1529.54   482.7 1535.92   507.2 1549.44   521.9 1553.91   531.8 1553.29
   536.7 1551.54   551.5 1540.76   561.3 1538.95   595.8 1542.05   625.3 1541.58
   664.8  1543.9   773.1  1554.9   787.9 1561.59   807.6 1576.39   837.2 1591.38
#Mann= 3 , 0 , 0
       0      .1       0   364.1    .045       0   379.1      .1       0
Bank Sta=364.1,379.1
XS Rating Curve= 0 ,0
Exp/Cntr=0.3,0.1

Type RM Length L Ch R = 1 ,8263.7  ,435.4,468.9,495.7
XS GIS Cut Line= 4
     1781415.057      193306.928     1781672.658      193365.215
     1781963.706      193163.013     1782325.045      193150.426
#Sta/Elev= 30
       0 1543.58    19.9  1542.5    54.8 1545.87    84.7 1551.46    99.7 1556.47
   114.6 1559.74   139.5 1562.53   169.4 1563.96   214.3  1562.9   249.2 1559.63
     299 1548.14     334 1534.73   363.9 1525.66   378.9 1525.39   393.9 1521.13
   427.1 1520.12   433.8 1519.79   442.1 1520.52   538.6 1521.62   583.6 1520.58
   638.3 1521.98   658.1 1524.68   697.8 1536.56   727.5 1541.54   757.2 1541.98
   841.4 1552.09   871.1 1553.28   890.9 1552.56   940.4 1554.68   980.1 1566.72
#Mann= 3 , 0 , 0
       0      .1       0   427.1    .045       0   442.1      .1       0
Bank Sta=427.1,442.1
XS Rating Curve= 0 ,0
Exp/Cntr=0.3,0.1

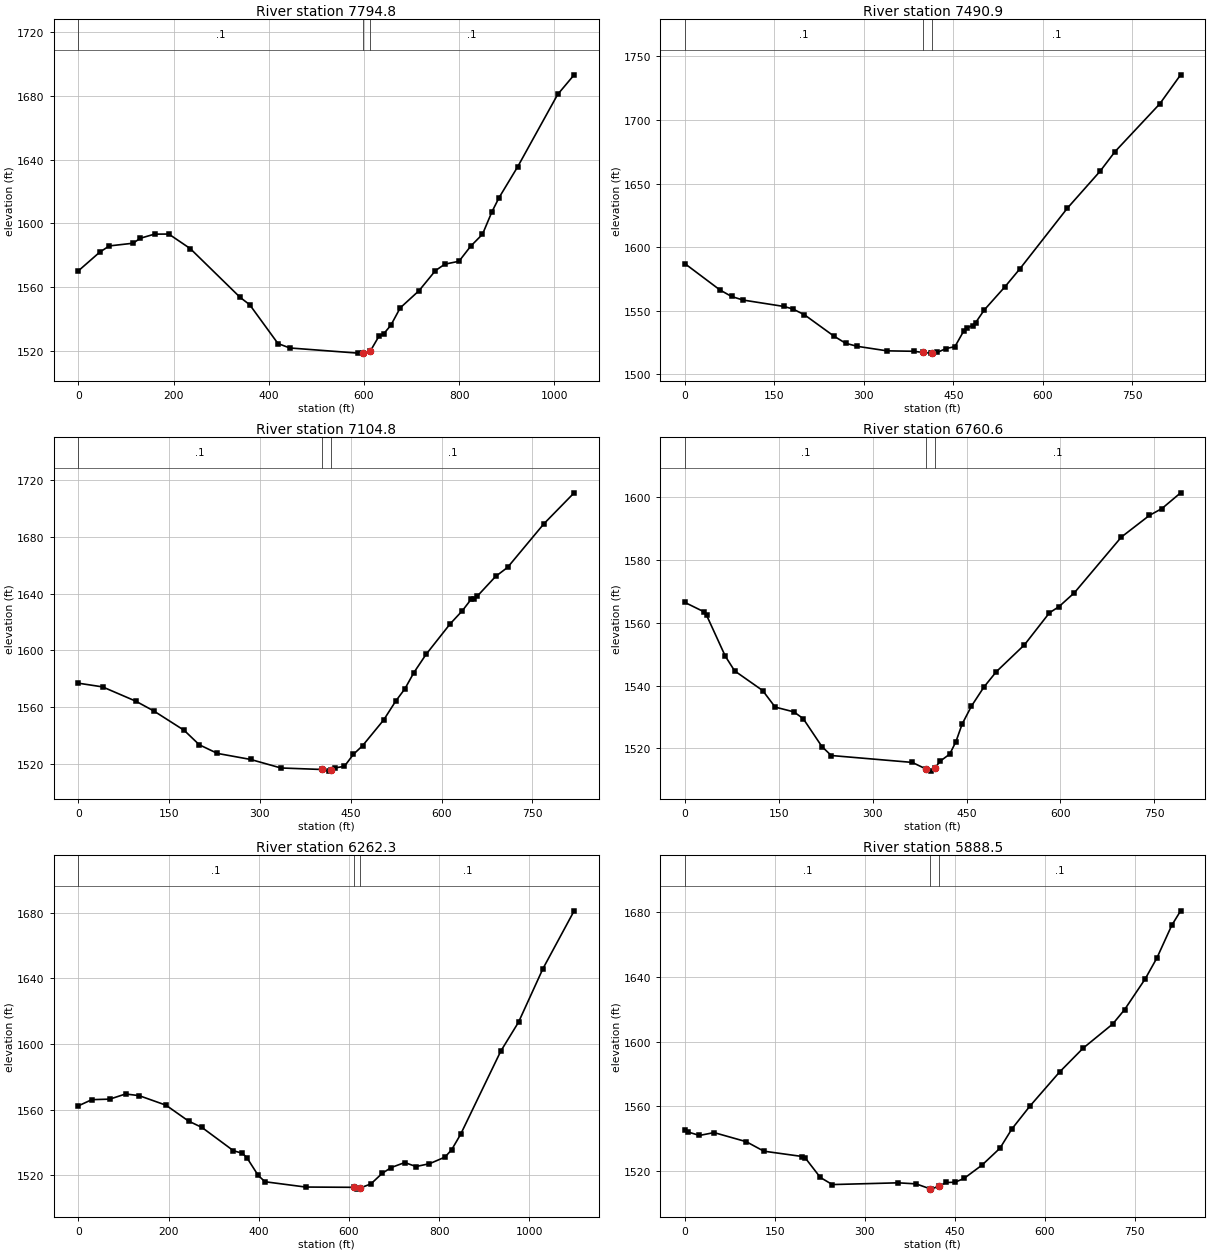
Type RM Length L Ch R = 1 ,7794.8  ,310.6,303.8,296.9
XS GIS Cut Line= 4
     1781305.019      193466.316     1781669.594      193481.634
     1782018.852      193644.008      1782310.05      193639.101
#Sta/Elev= 30
       0 1570.24      45 1581.97      65 1585.87     115 1587.56     130 1590.66
     160 1593.25     190  1593.3   234.9 1584.23   339.9 1553.62   359.9 1549.04
   419.2 1524.74   443.9 1521.96   587.1 1518.72   597.9 1518.96   612.9 1519.85
   631.5 1529.39   641.4 1530.87   656.2 1536.11     676 1547.06   715.5 1557.83
     750 1570.41   769.8 1574.46   799.4 1576.25   824.1 1585.73   848.8 1593.18
   868.5 1607.16   883.3 1615.97   922.8 1635.51  1006.7 1680.77  1041.3 1693.04
#Mann= 3 , 0 , 0
       0      .1       0   597.9    .045       0   612.9      .1       0
Bank Sta=597.9,612.9
XS Rating Curve= 0 ,0
Exp/Cntr=0.3,0.1

Type RM Length L Ch R = 1 ,7490.9  ,395.1,386.2,377.2
XS GIS Cut Line= 4
     1781377.947      193822.741     1781593.003      193830.892
     1781960.966      193878.352     1782200.657      193928.138
#Sta/Elev= 30
       0 1587.17    58.7 1566.51    78.3 1561.31    97.8 1558.49   166.3 1553.45
     181 1551.51   200.5 1546.94   249.8  1530.2   269.6 1524.52   289.4 1522.11
   338.9 1518.58   383.4 1518.25   399.9 1517.29   413.1 1516.79   414.9 1516.84
     423  1517.3   437.8 1520.39   452.7 1521.87   467.5 1534.18   472.4 1536.47
   482.3  1538.5   487.3 1540.67   502.1 1550.83   536.8 1569.06   561.5 1582.98
   641.2 1630.72   696.1 1659.77   721.1 1675.17   796.1 1712.72     831  1735.5
#Mann= 3 , 0 , 0
       0      .1       0   399.9    .045       0   414.9      .1       0
Bank Sta=399.9,414.9
XS Rating Curve= 0 ,0
Exp/Cntr=0.3,0.1

Type RM Length L Ch R = 1 ,7104.8  ,348.7,344.2,339.6
XS GIS Cut Line= 3
     1781422.145      194344.428     1781817.076      194236.172
     1782212.008      194127.916
#Sta/Elev= 30
       0 1576.91      40  1574.3    94.9 1564.24   124.8 1557.29   174.8 1543.69
   199.8 1533.51   229.7 1527.42   284.6 1523.17   334.6 1517.16     402  1516.1
   414.5 1514.94     417  1515.5   424.5 1517.25   439.5 1518.32   454.4 1526.79
   469.4 1532.81   504.4 1551.01   524.4 1564.38   539.3 1572.86   554.3  1584.4
   574.3 1597.16   614.2 1618.72   634.2  1627.9   649.2 1636.24   654.2 1636.52
   659.2 1638.33   689.2 1652.11   709.1 1658.53   769.1 1689.27     819 1711.04
#Mann= 3 , 0 , 0
       0      .1       0     402    .045       0     417      .1       0
Bank Sta=402,417
XS Rating Curve= 0 ,0
Exp/Cntr=0.3,0.1

Type RM Length L Ch R = 1 ,6760.6  ,494,498.3,502.6
XS GIS Cut Line= 3
     1781559.303      194743.863     1781994.343      194523.279
     1782270.072      194394.605
#Sta/Elev= 30
       0 1566.52    29.9 1563.59    34.8 1562.41    64.7 1549.37    79.6 1544.68
   124.4 1538.41   144.3 1533.14   174.2 1531.61   189.1 1529.47     219 1520.56
   233.9  1517.7   363.3  1515.5   385.1 1513.42   393.2 1512.72   400.1 1513.87
   408.1 1515.93   423.1 1518.13     433 1522.07     443 1527.73   457.9 1533.45
   477.8 1539.53   497.7 1544.44   542.6    1553   582.5 1563.21   597.5 1565.13
   622.4 1569.61   697.3 1587.34   742.2 1594.26   762.1 1596.43     792 1601.45
#Mann= 3 , 0 , 0
       0      .1       0   385.1    .045       0   400.1      .1       0
Bank Sta=385.1,400.1
XS Rating Curve= 0 ,0
Exp/Cntr=0.3,0.1

Type RM Length L Ch R = 1 ,6262.3  ,372.6,373.9,375.1
XS GIS Cut Line= 4
      1781548.58       195120.31      1781908.56      195066.696
      1782302.34      194953.322     1782582.566      194787.137
#Sta/Elev= 30
       0 1562.23    29.9    1566    69.8 1566.33   104.7 1569.46   134.6 1568.47
   194.4 1562.63   244.3 1552.98   274.2 1549.06     344 1534.88     364 1533.33
     374 1530.54   398.9 1519.84   413.9    1516   503.9 1512.77   610.5  1512.6
   618.8  1511.5   625.5 1512.24   648.8 1514.68   673.8 1521.12   693.8 1524.65
   723.8 1527.69   748.7 1525.27   778.7 1526.98   813.2 1531.03     828 1535.58
   847.8 1544.92   936.6 1595.48   976.1 1613.18  1030.4 1645.88  1099.5 1681.04
#Mann= 3 , 0 , 0
       0      .1       0   610.5    .045       0   625.5      .1       0
Bank Sta=610.5,625.5
XS Rating Curve= 0 ,0
Exp/Cntr=0.3,0.1

Type RM Length L Ch R = 1 ,5888.5  ,272,269.7,267.5
XS GIS Cut Line= 4
     1781803.907      195399.801     1781958.345      195422.847
     1782372.087      195328.282     1782616.495      195297.517
#Sta/Elev= 30
       0 1545.75     4.9 1544.28    24.4 1542.08    48.8 1543.85   102.5 1538.24
   131.8 1532.39   196.1  1529.1   201.1 1528.11     226  1516.2     246  1511.8
   355.9 1512.88   385.8 1512.22   409.1 1509.18   410.8 1508.99   424.1 1510.87
   435.8 1513.08   450.7 1513.24   465.7 1515.58   495.7 1523.82   525.6 1534.21
   545.6 1546.15   575.6  1560.2   624.9 1581.15   664.3  1595.9   713.6 1610.78
   733.3 1619.59   767.8 1638.59   787.5 1651.63   812.1 1671.64   826.9 1680.58
#Mann= 3 , 0 , 0
       0      .1       0   409.1    .045       0   424.1      .1       0
Bank Sta=409.1,424.1
XS Rating Curve= 0 ,0
Exp/Cntr=0.3,0.1

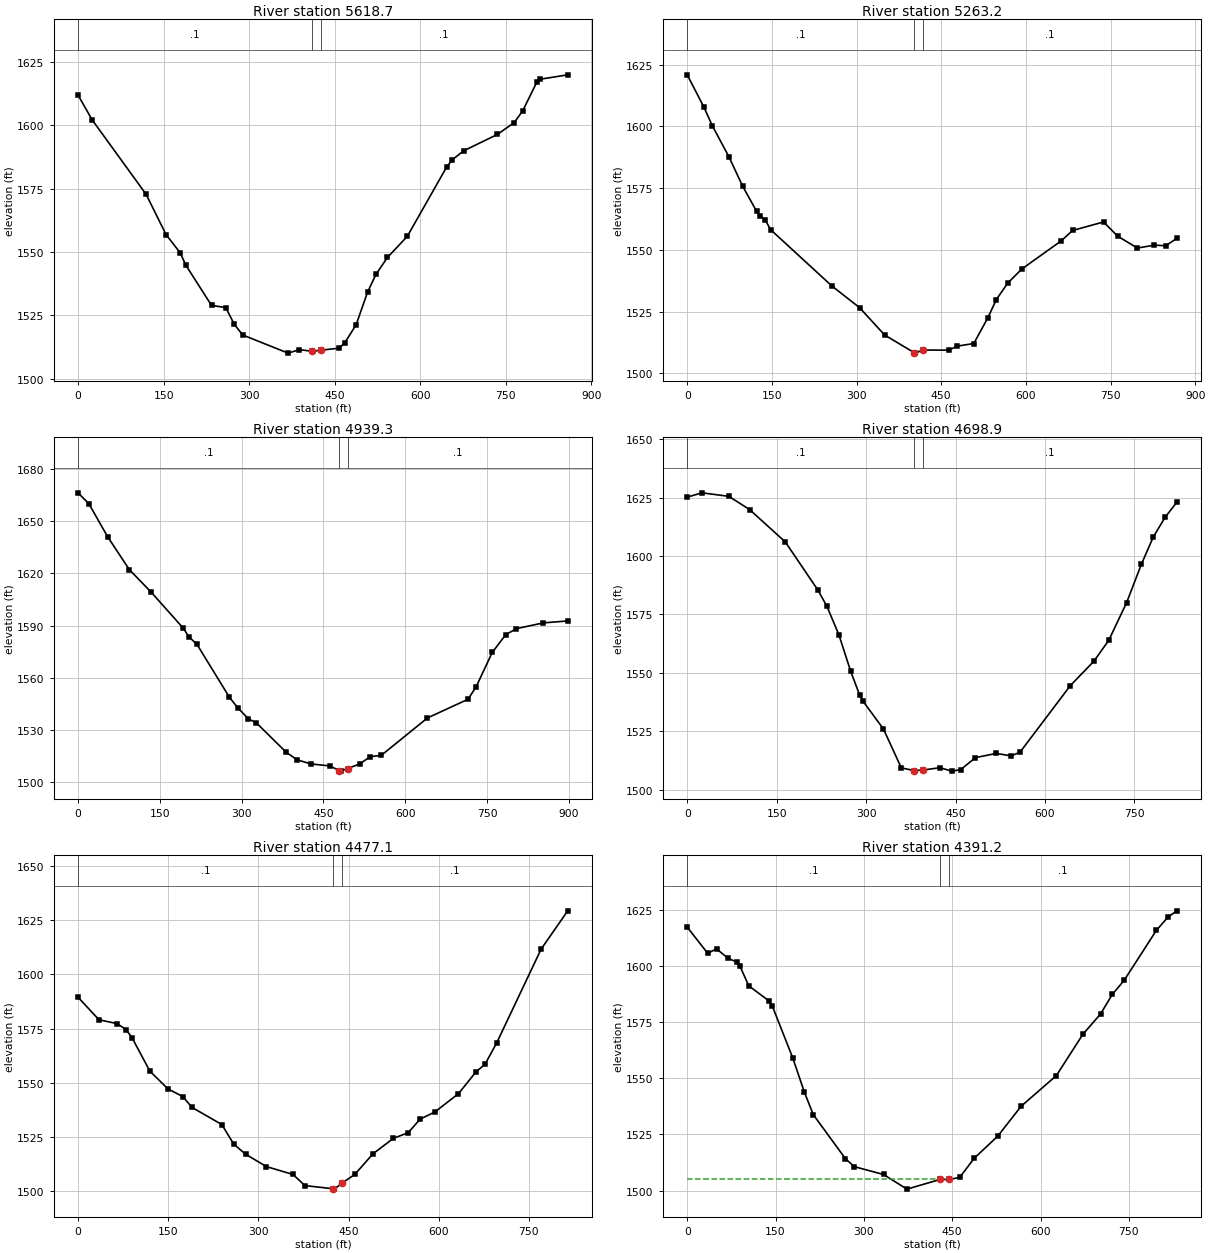
Type RM Length L Ch R = 1 ,5618.7  ,347.2,355.5,362.1
XS GIS Cut Line= 4
     1781879.712      195819.338     1782084.721      195687.088
     1782391.087      195583.689     1782651.498      195453.483
#Sta/Elev= 30
       0 1611.93    24.9 1602.09   119.5 1572.69   154.3 1556.86   179.2 1549.63
   189.2  1544.7     234 1528.91   258.9 1528.06   273.8  1521.5   288.7 1517.23
   368.3 1510.07   388.2 1511.45   410.5 1510.79   425.5 1511.22   457.9 1512.03
   467.8  1514.2   487.7 1521.34   507.6 1534.19   522.5 1541.22   542.4 1547.83
   577.2 1556.15   646.3 1583.55   656.1 1586.39   675.9 1589.91   735.1 1596.37
   764.7 1601.08   779.5 1605.69   804.2 1616.99   809.1 1618.14   858.5 1619.91
#Mann= 3 , 0 , 0
       0      .1       0   410.5    .045       0   425.5      .1       0
Bank Sta=410.5,425.5
XS Rating Curve= 0 ,0
Exp/Cntr=0.3,0.1

Type RM Length L Ch R = 1 ,5263.2  ,317.3,323.9,323
XS GIS Cut Line= 4
     1781874.094      196004.943     1782191.949      195966.647
     1782379.598      195970.477      1782724.26      195867.078
#Sta/Elev= 30
       0  1620.9    29.6 1607.81    44.3 1600.38    73.9 1587.72    98.5  1575.7
   123.1  1565.6   128.1 1563.92   137.9  1562.3   147.8 1558.21   256.1 1535.46
   305.4 1526.64   349.8 1515.56   402.7 1508.36   404.1 1508.23   417.7  1509.5
   463.4 1509.42   478.2 1511.05   507.8 1512.12   532.8  1522.6   547.8 1529.94
   567.8 1536.55   592.8 1542.27   662.8  1553.7   682.8 1557.88   737.7 1561.33
   762.7 1555.57   797.7 1550.77   827.7 1551.95   847.7 1551.69   867.7 1554.71
#Mann= 3 , 0 , 0
       0      .1       0   402.7    .045       0   417.7      .1       0
Bank Sta=402.7,417.7
XS Rating Curve= 0 ,0
Exp/Cntr=0.3,0.1

Type RM Length L Ch R = 1 ,4939.3  ,238.4,240.4,241.5
XS GIS Cut Line= 4
     1781862.605      196261.524     1782245.563       196207.91
     1782513.633      196230.888      1782720.43      196104.512
#Sta/Elev= 30
       0 1666.29    19.8 1660.06    54.5 1640.98    94.2 1622.16   133.9 1609.33
   193.4 1588.42   203.3  1583.6   218.1 1579.29   277.6 1548.91   292.5    1543
   312.3 1536.56   327.2 1534.15   381.7 1517.36   401.6 1513.02   426.6 1510.63
   461.4 1509.48   479.4 1506.79   481.4 1506.48   494.4 1507.97   516.2 1510.56
   536.2 1514.82   556.1 1515.52   640.8 1537.02   715.1 1547.73   729.9 1554.78
   759.6 1574.61   784.3 1584.82   804.1 1588.31   853.6 1591.62   898.1 1592.72
#Mann= 3 , 0 , 0
       0      .1       0   479.4    .045       0   494.4      .1       0
Bank Sta=479.4,494.4
XS Rating Curve= 0 ,0
Exp/Cntr=0.3,0.1

Type RM Length L Ch R = 1 ,4698.9  ,225.6,221.9,219.1
XS GIS Cut Line= 3
      1781893.39      196371.248     1782295.651      196445.059
     1782703.592      196505.977
#Sta/Elev= 30
       0 1625.17    24.9    1627    69.8  1625.5   104.7 1619.82   164.6 1605.96
   219.4  1585.3   234.4  1578.4   254.4 1566.25   274.3 1550.54   289.3 1540.41
   294.3 1538.02   329.2  1525.9   359.1 1509.29   380.3 1508.16   395.3 1508.36
   423.9 1509.37   443.8  1507.9   458.7 1508.55   483.5 1513.68   518.3 1515.48
   543.2 1514.44   558.1 1515.96   642.5 1544.46   682.3 1554.99   707.1  1563.9
     737 1580.01   761.8 1596.44   781.7 1608.08   801.6 1616.54   821.4 1623.03
#Mann= 3 , 0 , 0
       0      .1       0   380.3    .045       0   395.3      .1       0
Bank Sta=380.3,395.3
XS Rating Curve= 0 ,0
Exp/Cntr=0.3,0.1

Type RM Length L Ch R = 1 ,4477.1  ,84.1,85.9,87.7
XS GIS Cut Line= 4
     1781885.583      196613.845     1782168.971      196632.993
     1782429.383      196632.993     1782697.453      196598.527
#Sta/Elev= 30
       0 1589.46    34.9 1579.07    64.8 1577.32    79.7 1574.59    89.7 1570.88
   119.6 1555.38   149.5 1547.24   174.4 1543.68   189.4 1538.72   239.2  1530.8
   259.1 1521.74     279 1517.08   313.5 1511.41   357.7 1507.78   377.4 1502.66
   424.2 1501.21   426.5 1501.03   439.2 1503.78   460.9 1507.91   490.4 1517.25
   524.8 1524.46   549.4 1527.05     569 1533.28   593.6 1536.58   632.9 1545.02
   662.4 1555.17   677.1 1558.56   696.8  1568.6   770.5 1611.68   814.7 1629.28
#Mann= 3 , 0 , 0
       0      .1       0   424.2    .045       0   439.2      .1       0
Bank Sta=424.2,439.2
XS Rating Curve= 0 ,0
Exp/Cntr=0.3,0.1

Type RM Length L Ch R = 1 ,4391.2  ,162,161.3,161
XS GIS Cut Line= 4
     1781884.475         196707.     1782103.427      196700.296
      1782440.43      196727.103     1782693.897      196832.764
#Sta/Elev= 30
       0  1617.4    34.8 1605.72    49.8 1607.71    69.7 1603.43    84.6 1601.78
    89.6 1599.96   104.6 1591.22   139.4 1584.42   144.4 1582.31   179.2 1559.15
   199.1 1543.79   214.1 1533.84   268.8 1514.19   283.7 1510.68   333.4 1507.18
   373.2 1500.66   429.7 1504.99   444.7 1504.97   462.7 1505.85   487.5 1514.44
   527.3 1524.23   567.1 1537.58     627 1551.26     672 1569.65   701.9 1578.66
   721.9 1587.38   741.9 1593.62   796.8 1615.94   816.8 1621.94   831.7 1624.65
#Mann= 3 , 0 , 0
       0      .1       0   429.7    .045       0   444.7      .1       0
#XS Ineff= 2 , 0
          421.61 1505.17
Permanent Ineff=
       F       F
Bank Sta=429.7,444.7
XS Rating Curve= 0 ,0
Exp/Cntr=0.3,0.1

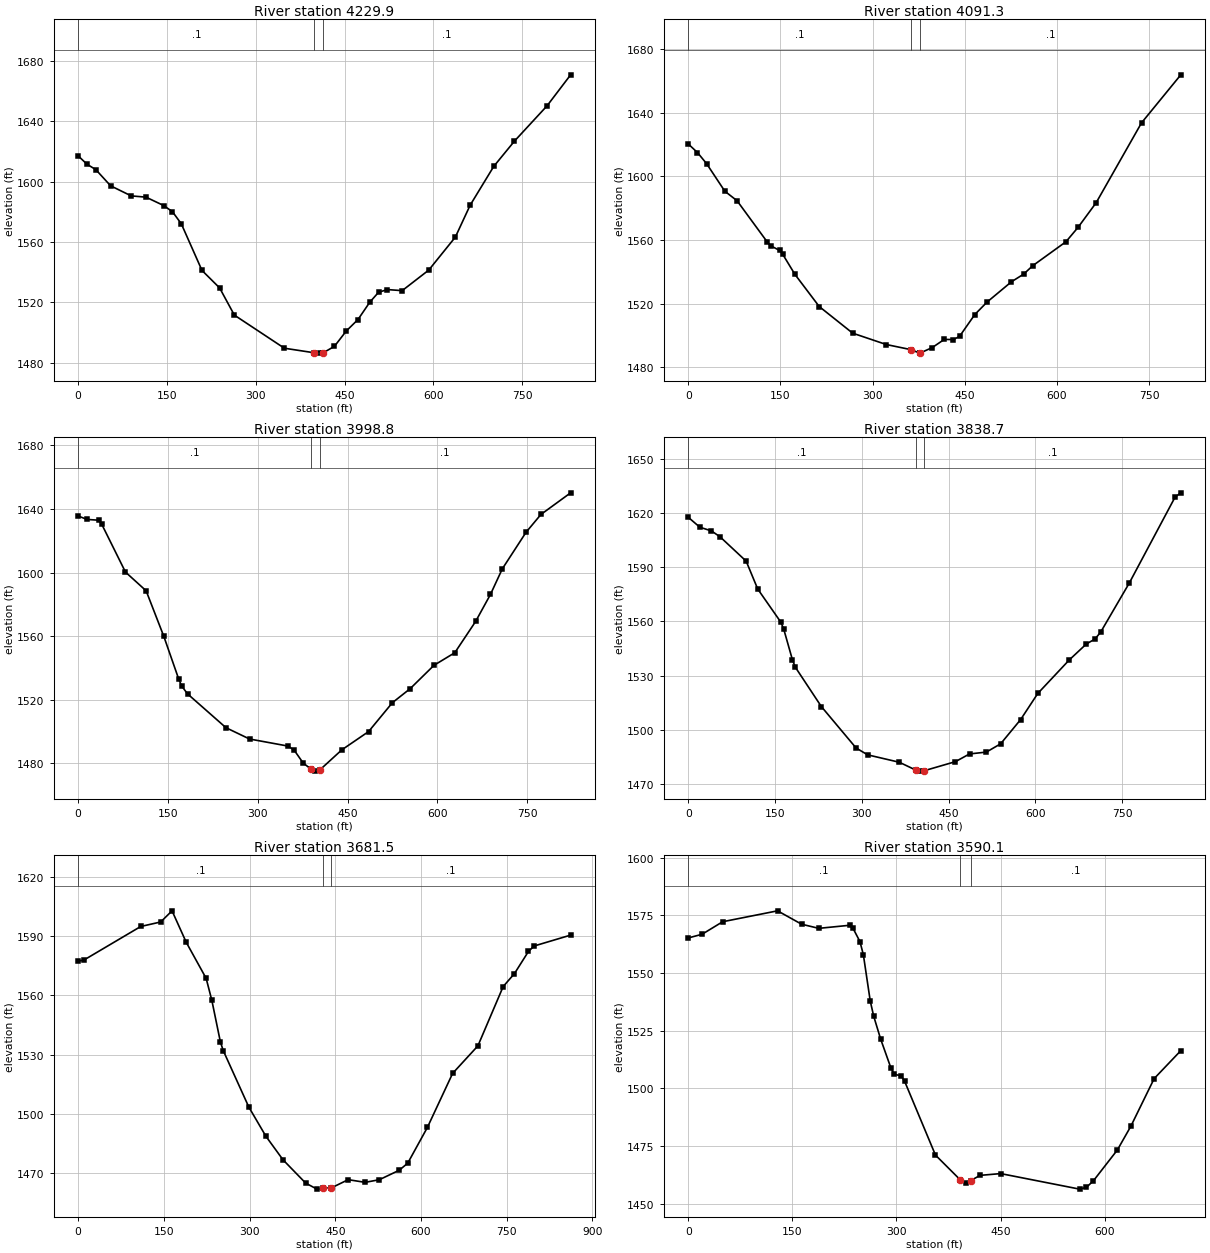
Type RM Length L Ch R = 1 ,4229.9  ,138.8,138.6,137.9
XS GIS Cut Line= 4
     1781881.087      196861.813     1782100.039      196855.109
     1782437.042      196881.916     1782690.508      196987.577
#Sta/Elev= 30
       0 1617.13    14.9 1611.58    29.9 1607.96    54.8 1597.26    89.6 1590.57
   114.5 1589.74   144.4 1584.18   159.3 1580.05   174.2 1572.06   209.1 1541.14
   238.9 1529.53   263.8 1511.49   348.3 1489.53   398.9  1486.5     408 1486.28
   413.9 1486.52   432.8 1490.78   452.7 1500.91   472.6 1508.58   492.5 1520.05
   507.4 1526.67   522.3 1528.43   547.2 1527.72   592.1 1541.36     637 1563.23
     662 1584.39   701.9 1610.15   736.9 1626.93   791.8 1650.27   831.7 1670.87
#Mann= 3 , 0 , 0
       0      .1       0   398.9    .045       0   413.9      .1       0
Bank Sta=398.9,413.9
XS Rating Curve= 0 ,0
Exp/Cntr=0.3,0.1

Type RM Length L Ch R = 1 ,4091.3  ,93,92.5,92
XS GIS Cut Line= 4
     1781883.329      196998.457     1782160.746       196994.19
     1782418.957      197004.859      1782683.57      197028.333
#Sta/Elev= 30
       0 1620.38    14.9    1615    29.7 1608.04    59.4 1590.69    79.3  1584.7
   128.8 1558.57   133.8 1556.43   148.6 1553.42   153.6 1551.03   173.4 1538.42
     213 1518.16   267.5 1501.38   322.2 1494.24   361.7 1491.07   376.7 1488.86
   376.8 1488.83   396.7 1492.26   416.6 1497.46   431.5 1497.36   441.4 1499.36
   466.3 1513.13   486.2 1520.95   525.9 1533.72   545.7 1538.52   560.5 1543.81
   614.6  1558.9   634.3 1567.96   663.8 1583.48   737.6  1633.7   801.5 1663.91
#Mann= 3 , 0 , 0
       0      .1       0   361.7    .045       0   376.7      .1       0
Bank Sta=361.7,376.7
XS Rating Curve= 0 ,0
Exp/Cntr=0.3,0.1

Type RM Length L Ch R = 1 ,3998.8  ,160,160.1,160.2
XS GIS Cut Line= 4
     1781870.525      197074.964     1782156.478      197087.767
     1782459.502      197092.035     1782692.106      197077.097
#Sta/Elev= 30
       0 1635.63    14.8 1633.47    34.6 1632.97    39.5 1630.34      79 1600.35
   113.5 1588.56   143.1 1559.82   167.8 1533.14   172.7 1528.75   182.6 1523.72
   246.8 1502.42   286.2  1495.3   350.8 1490.83   360.8 1488.24   375.7 1480.22
   388.2 1476.53   395.5 1475.09   403.2 1475.71   440.2 1488.45     485 1499.98
   524.7 1518.13   554.5    1527   594.2 1541.67     629 1549.61   663.7 1569.25
   688.5 1586.27   708.3 1602.37     748 1625.41   772.8  1636.6   822.4 1650.21
#Mann= 3 , 0 , 0
       0      .1       0   388.2    .045       0   403.2      .1       0
Bank Sta=388.2,403.2
XS Rating Curve= 0 ,0
Exp/Cntr=0.3,0.1

Type RM Length L Ch R = 1 ,3838.7  ,151.9,157.2,162.6
XS GIS Cut Line= 4
     1781865.144       197164.45     1782216.334      197243.598
     1782376.382         197250.     1782685.253      197130.208
#Sta/Elev= 30
       0 1617.57      20  1612.1      40 1610.07      55 1606.77     100 1593.34
     120 1577.92     160 1559.57     165 1555.69     180 1538.77     185 1534.68
     230 1512.91     290 1490.01     310  1486.2   364.8  1482.1   392.8 1477.85
   398.8 1477.19   407.8 1477.41   461.9 1482.44   486.2  1486.7   515.3 1487.72
     540  1492.3   574.6 1505.72   604.2 1520.14   658.6 1538.68   688.3 1547.55
   703.1 1550.25     713 1554.11   762.5 1581.27   841.6 1628.76   851.5 1631.14
#Mann= 3 , 0 , 0
       0      .1       0   392.8    .045       0   407.8      .1       0
Bank Sta=392.8,407.8
XS Rating Curve= 0 ,0
Exp/Cntr=0.3,0.1

Type RM Length L Ch R = 1 ,3681.5  ,96.1,91.4,86.8
XS GIS Cut Line= 4
     1781843.468      197344.477     1782195.796      197373.238
     1782411.508      197430.761     1782673.956       197319.31
#Sta/Elev= 30
       0 1577.27      10 1577.79   109.5 1594.78   144.4 1597.06   164.3  1602.7
   189.2 1586.75     224 1568.54     234 1557.36   248.9  1536.4   253.9 1532.01
   298.7 1503.42   328.6 1488.65   358.5 1476.76   398.2 1464.96     418 1461.92
   428.1 1462.37   443.1 1462.54   472.6 1466.71   502.3 1465.35   527.1 1466.68
   561.9 1471.47   576.8 1475.05   611.2 1493.13   655.4 1520.48   699.6 1534.39
   743.9 1564.42   763.6 1570.95   788.1 1582.16     798 1584.91   861.9 1590.41
#Mann= 3 , 0 , 0
       0      .1       0   428.1    .045       0   443.1      .1       0
Bank Sta=428.1,443.1
XS Rating Curve= 0 ,0
Exp/Cntr=0.3,0.1

Type RM Length L Ch R = 1 ,3590.1  ,52.8,51,49.2
XS GIS Cut Line= 4
      1781832.13      197405.154     1782142.989      197465.383
     1782454.101      197483.224     1782535.448       197477.04
#Sta/Elev= 30
       0 1565.22    19.8 1566.81    49.5 1572.25   128.6 1576.98   163.3 1571.17
     188 1569.38   232.5 1570.71   237.5 1569.32   247.4 1563.61   252.3 1557.89
   262.2 1537.86   267.2 1531.23   277.1 1521.42   291.9 1508.88   296.8 1506.09
   306.8 1505.36   311.7 1503.07   356.2 1471.01   391.7 1460.34   400.7 1458.93
   406.7 1459.88   420.5 1462.21   450.2 1462.98     564 1456.24   573.8 1457.03
   583.8 1459.83   618.4 1473.24   637.9 1483.57   671.4 1504.19   709.8 1516.31
#Mann= 3 , 0 , 0
       0      .1       0   391.7    .045       0   406.7      .1       0
#XS Ineff= 2 , 0
                          449.25          1462.9
Permanent Ineff=
       F       F
Bank Sta=391.7,406.7
XS Rating Curve= 0 ,0
Exp/Cntr=0.3,0.1

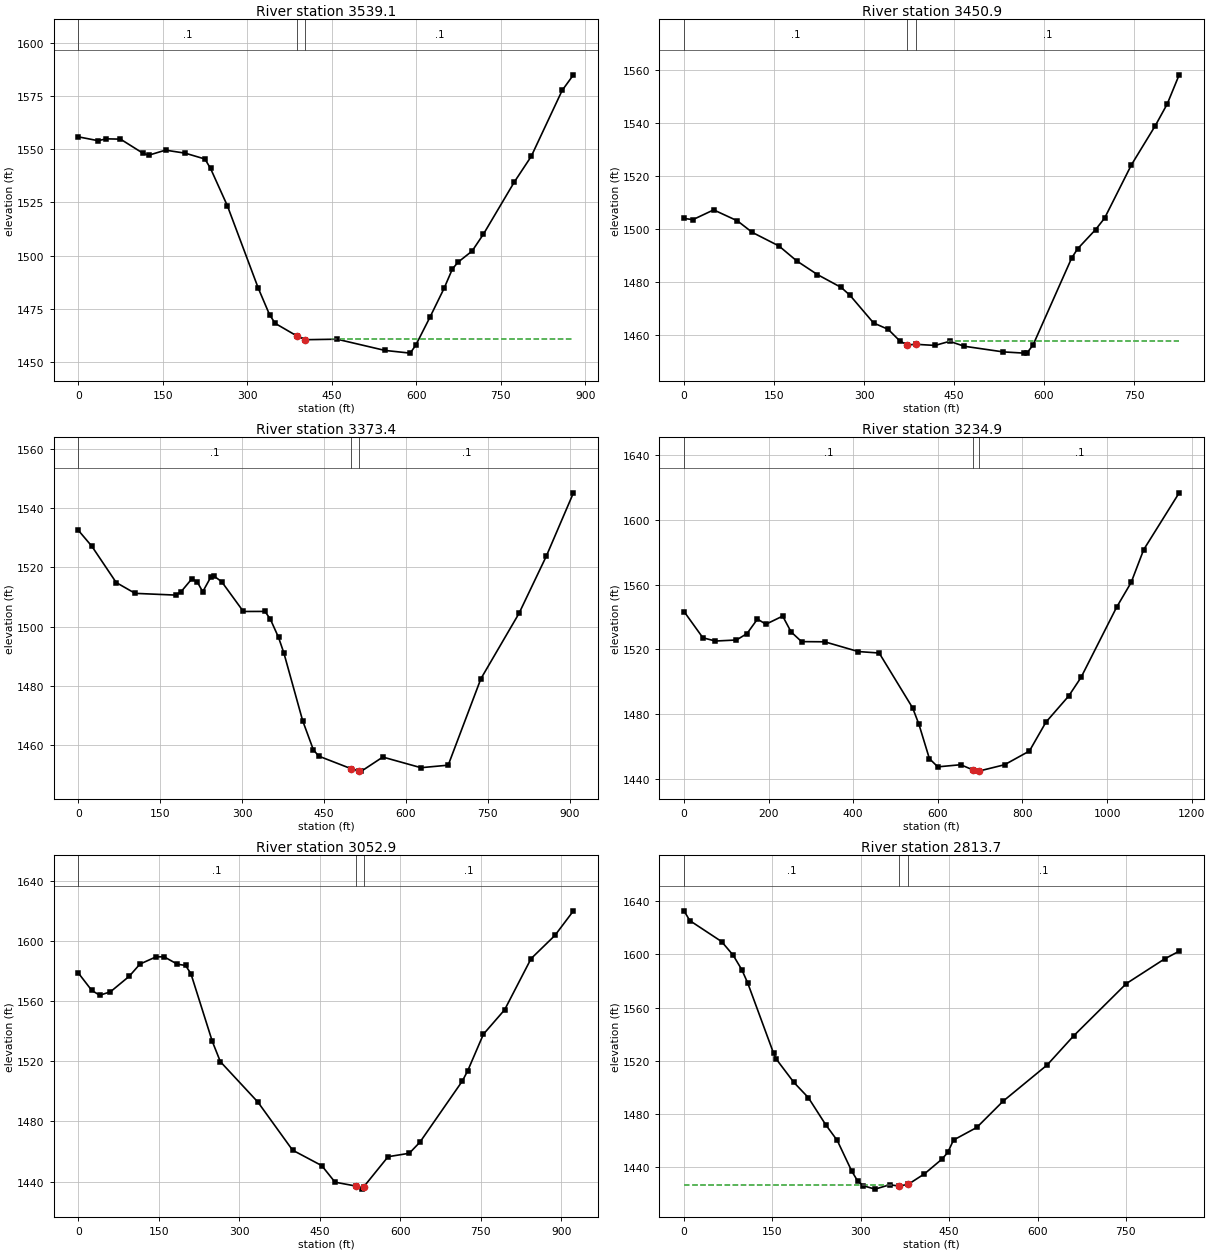
Type RM Length L Ch R = 1 ,3539.1  ,91.7,88.2,88.4
XS GIS Cut Line= 4
     1781833.135       197444.65     1782143.238      197522.176
     1782477.611      197513.146      1782690.92      197442.149
#Sta/Elev= 30
       0 1555.78      35 1553.98    49.9 1554.84    74.9  1554.7   114.9 1548.07
   124.9 1547.16   154.8 1549.54   189.8 1548.12   224.8 1545.38   234.7 1540.98
   264.7 1523.42   319.6 1484.73   339.6 1472.32   349.6 1468.29   388.3 1462.36
   403.3 1460.65   459.4 1460.88   544.3 1455.62   589.2 1454.35   599.2 1458.12
   624.2 1471.16   649.2 1484.66   664.1 1493.81   674.1 1496.99   699.1 1502.22
   719.1  1510.1     774 1534.59     804 1546.59     859 1577.58     879 1584.86
#Mann= 3 , 0 , 0
       0      .1       0   388.3    .045       0   403.3      .1       0
#XS Ineff= 2 , 0
                          449.07         1461.11
Permanent Ineff=
       F       F
Bank Sta=388.3,403.3
XS Rating Curve= 0 ,0
Exp/Cntr=0.3,0.1

Type RM Length L Ch R = 1 ,3450.9  ,98.8,77.5,52.3
XS GIS Cut Line= 4
     1781857.387      197591.669      1782137.16      197624.698
     1782312.018      197580.012     1782657.849      197469.268
#Sta/Elev= 30
       0 1503.95    14.8  1503.5    49.4 1507.18      89 1503.04   113.7  1498.7
   158.2 1493.57   187.8 1487.95   222.4 1482.78     262 1477.93   276.8 1474.92
   315.9 1464.53   340.2 1462.14   359.8 1457.74   371.9 1456.26   386.9 1456.48
   418.3 1456.06   442.7 1457.61   467.2 1455.75   531.8 1453.63   566.7 1453.16
   571.6 1453.24   581.6 1456.15   646.2 1489.07   656.2 1492.55     686 1499.75
     701 1504.06   745.7 1524.17   785.5 1538.93   805.4 1547.12   825.3 1558.11
#Mann= 3 , 0 , 0
       0      .1       0   371.9    .045       0   386.9      .1       0
#XS Ineff= 2 , 0
                          439.33         1457.57
Permanent Ineff=
       F       F
Bank Sta=371.9,386.9
XS Rating Curve= 0 ,0
Exp/Cntr=0.3,0.1

Type RM Length L Ch R = 1 ,3373.4  ,141.3,138.5,135.7
XS GIS Cut Line= 4
     1781867.101      197712.127     1782234.304       197768.47
     1782312.018      197599.441     1782642.306      197486.754
#Sta/Elev= 30
       0  1532.5    24.8  1527.1    69.4 1514.85     104  1511.2   178.3 1510.61
   188.2 1511.76     208 1516.13     218 1514.99   227.8 1511.74   242.7 1516.73
   247.7 1517.13   262.5 1515.13   302.2 1505.08   341.8  1505.1   351.7 1502.44
   366.6 1496.32   376.4 1491.04   410.7 1468.24   430.2 1458.45     440 1456.26
   499.3 1452.01   514.3 1451.21   518.4 1451.18   557.5 1455.93   627.3 1452.34
   677.2 1453.19     737 1482.36   806.8 1504.43   856.7 1523.71   906.5 1545.14
#Mann= 3 , 0 , 0
       0      .1       0   499.3    .045       0   514.3      .1       0
#XS Ineff= 2 , 0
                           558.9         1455.83
Permanent Ineff=
       F       F
Bank Sta=499.3,514.3
XS Rating Curve= 0 ,0
Exp/Cntr=0.3,0.1

Type RM Length L Ch R = 1 ,3234.9  ,178.1,182,185.8
XS GIS Cut Line= 5
     1781866.978      197766.092     1782362.384      197869.022
     1782443.018      197615.024     1782603.391      197572.192
     1782758.443      197399.635
#Sta/Elev= 30
       0 1543.36    44.6 1527.11    74.4 1525.11     124 1525.76   148.8  1529.7
   173.6 1538.69   193.5 1535.49   233.2 1540.53     253 1530.77   277.8 1524.75
   332.4 1524.64   411.7 1518.62   461.3  1517.7   540.5 1483.73   555.3 1473.59
     580 1452.42   599.8 1447.34     654 1448.66   683.3 1445.41   693.5  1444.7
   698.3 1444.81   757.7 1448.65   816.4 1457.12   855.5 1474.98   909.2  1491.1
   938.5 1502.65  1022.4 1545.95  1056.9 1561.33  1086.5 1581.58  1170.4 1616.72
#Mann= 3 , 0 , 0
       0      .1       0   683.3    .045       0   698.3      .1       0
#XS Ineff= 2 , 0
           653.9 1448.59
Permanent Ineff=
       F       F
Bank Sta=683.3,698.3
XS Rating Curve= 0 ,0
Exp/Cntr=0.3,0.1

Type RM Length L Ch R = 1 ,3052.9  ,241.7,239.3,236.9
XS GIS Cut Line= 4
     1782188.087      198066.846     1782518.187      197890.126
     1782648.838      197635.108     1782781.774      197410.109
#Sta/Elev= 30
       0  1578.9      25 1567.31    39.9 1564.04    59.9 1566.37    94.8 1576.67
   114.8 1584.81   144.8 1589.62   159.8 1589.65   184.7 1584.71   199.7 1583.91
   209.7  1578.5   249.6 1533.32   264.6 1519.82   334.5 1492.91   399.1  1460.9
   453.5 1450.57   478.2 1439.56     517 1436.97   527.6 1434.93     532 1436.63
     577 1456.52   616.5 1458.81   636.3 1466.19   715.2 1506.85   725.1 1513.55
   754.6 1538.11   794.1 1554.37   843.4 1588.46   887.8  1603.9   922.3 1620.28
#Mann= 3 , 0 , 0
       0      .1       0     517    .045       0     532      .1       0
Bank Sta=517,532
XS Rating Curve= 0 ,0
Exp/Cntr=0.3,0.1

Type RM Length L Ch R = 1 ,2813.7  ,193.1,199.8,206.5
XS GIS Cut Line= 4
     1782571.899      198223.821     1782715.218      198037.071
     1782811.608      197783.427     1783034.736      197535.303
#Sta/Elev= 30
       0 1632.75     9.8 1625.39    63.8 1609.63    83.4 1599.39    98.1 1588.45
   107.9 1578.72     152 1525.67   156.9 1521.08   186.4  1503.8   210.9 1492.37
   240.3 1472.08   260.1  1460.1   284.7 1437.04   294.6 1429.74   304.5 1426.04
   324.2 1423.54   348.9 1426.79   365.5 1425.87   380.5 1427.15   408.1 1435.03
   437.7 1446.06   447.6 1451.08   457.4 1460.44   496.9 1469.91   541.6 1489.66
   616.3 1516.86   661.1 1538.67   750.8 1578.07   815.5 1596.56   840.4  1602.4
#Mann= 3 , 0 , 0
       0      .1       0   365.5    .045       0   380.5      .1       0
#XS Ineff= 2 , 0
          353.81 1426.96
Permanent Ineff=
       F       F
Bank Sta=365.5,380.5
XS Rating Curve= 0 ,0
Exp/Cntr=0.3,0.1