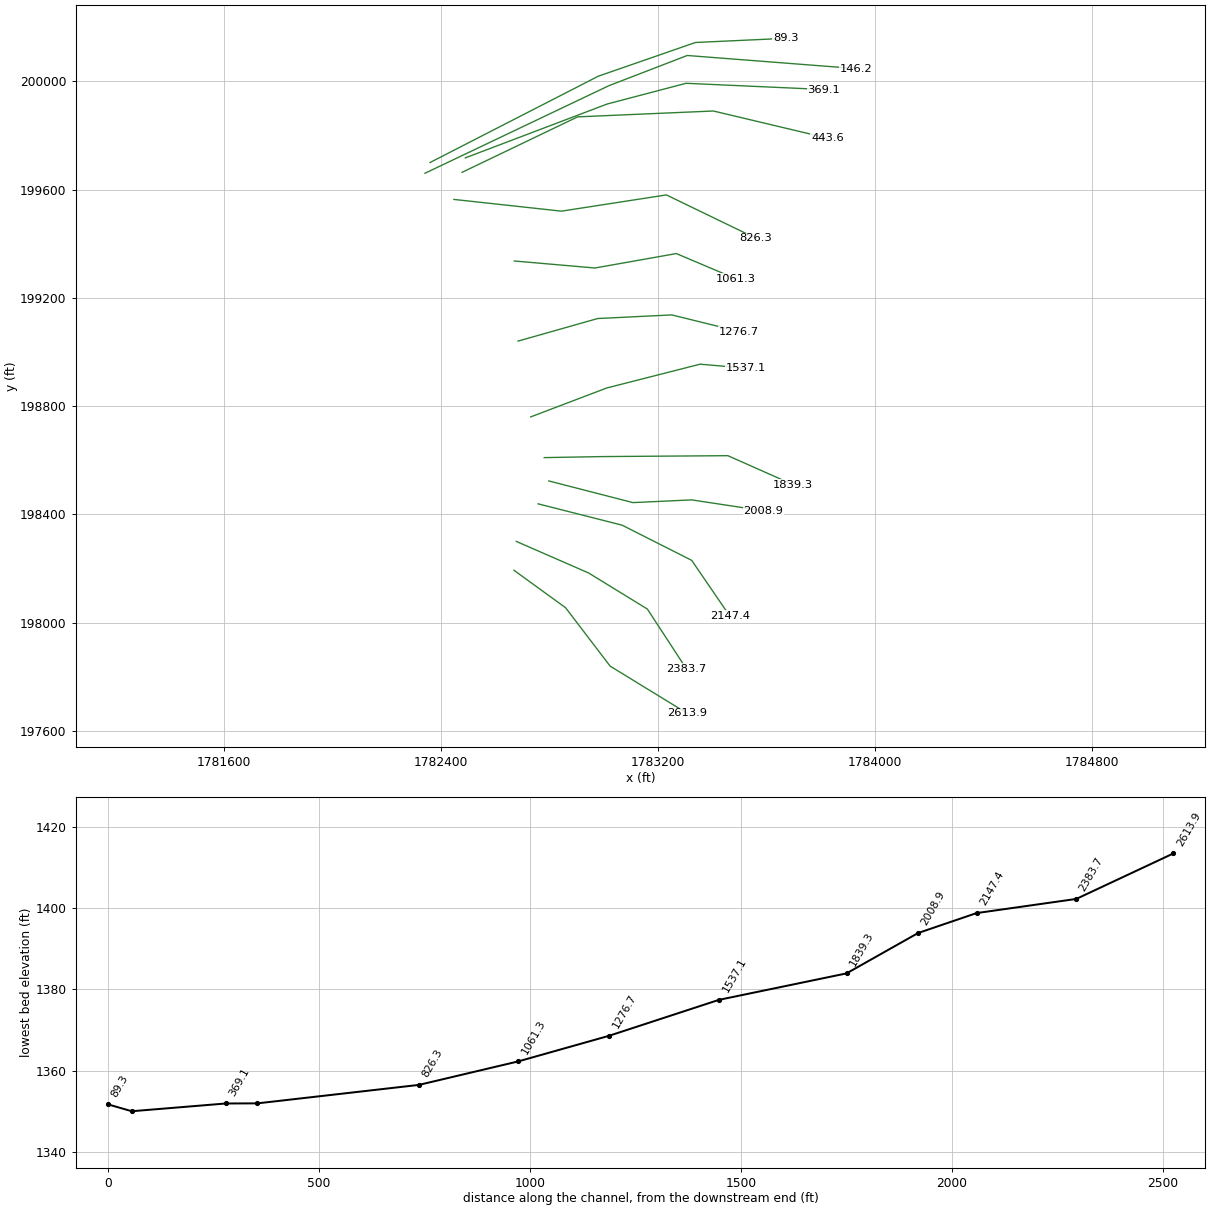
HEC-RAS study BrierCr.prj: BrierCr

--- BrierCr.g01 (geometry) --- (continued)

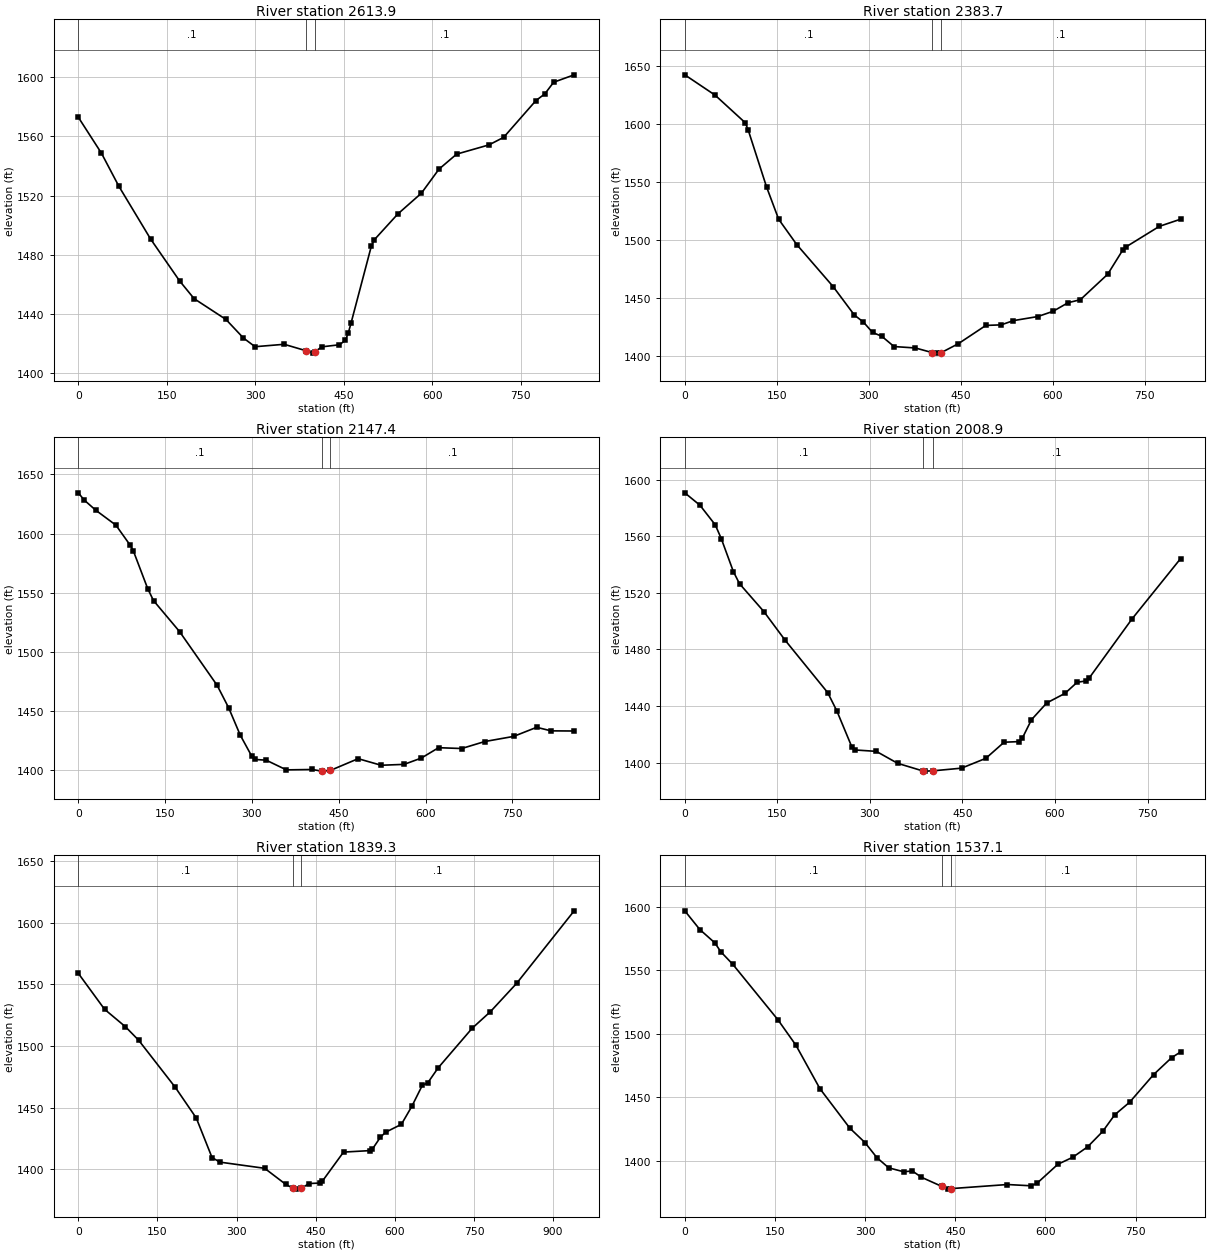
Type RM Length L Ch R = 1 ,2613.9  ,221.5,230.2,238.9
XS GIS Cut Line= 4
     1782669.559      198193.663     1782859.967      198055.242
     1783024.352      197839.362     1783308.701      197664.728
#Sta/Elev= 30
       0 1572.95    39.2 1548.65    68.7 1526.31   122.6 1490.59   171.6 1462.37
   196.2 1450.36   250.2  1436.3   279.8 1423.76   299.5 1417.87   348.9  1419.5
   385.9 1415.15   398.2 1413.53   400.9 1414.53     413  1417.8   442.6 1419.18
   452.5 1422.15   457.4 1426.89   462.4 1434.08   496.9 1486.27   501.8 1490.21
   541.6 1507.62   581.5 1521.64   611.3  1537.9   641.2 1548.04     696 1554.28
   720.9 1559.38   775.7 1584.28   790.6 1588.71   805.6 1596.62   840.4 1601.64
#Mann= 3 , 0 , 0
       0      .1       0   385.9    .045       0   400.9      .1       0
#XS Ineff= 2 , 0
          348.22 1419.41
Permanent Ineff=
       F       F
Bank Sta=385.9,400.9
XS Rating Curve= 0 ,0
Exp/Cntr=0.3,0.1

Type RM Length L Ch R = 1 ,2383.7  ,234.6,236.3,238
XS GIS Cut Line= 4
     1782678.235       198300.25     1782944.982      198183.548
     1783161.714      198050.174      1783305.09      197830.108
#Sta/Elev= 30
       0 1642.25    49.4 1624.72    98.7 1600.86   103.6 1594.28   133.2 1545.71
     153 1517.74   182.6 1495.84   241.8 1459.68   276.4 1435.16   291.2 1429.06
   306.1 1420.14   321.1 1416.85   341.1 1407.98     376 1406.75   403.3 1402.78
   410.9 1402.31   418.3 1402.83   445.8 1410.39   490.8  1426.2   515.7 1426.68
   535.7 1430.34   575.4 1433.84   600.2 1438.33   624.9  1445.8   644.8 1448.36
   689.4 1470.32   714.1  1491.3   719.1 1493.85   773.6 1511.61   808.3 1517.79
#Mann= 3 , 0 , 0
       0      .1       0   403.3    .045       0   418.3      .1       0
Bank Sta=403.3,418.3
XS Rating Curve= 0 ,0
Exp/Cntr=0.3,0.1

Type RM Length L Ch R = 1 ,2147.4  ,126.8,138.4,150.1
XS GIS Cut Line= 4
     1782758.559      198439.097     1783068.352      198360.268
     1783325.096      198230.228     1783465.527      198024.463
#Sta/Elev= 30
       0 1634.46      10 1628.39      30 1619.78    64.9 1607.09    89.9 1589.91
    94.9 1585.48   119.9 1553.27   129.9  1543.2   174.8 1517.02   239.8 1471.46
   259.7 1452.46   279.7 1429.32   299.7 1411.38   304.7 1408.71   324.6 1408.09
   359.4 1399.88     404  1400.2   420.4 1398.82   435.4  1399.4   483.4 1409.36
   523.1 1403.79   562.8 1404.54   592.6 1409.89   622.4 1418.66   662.3 1417.96
   702.1 1423.87     752 1428.22   791.8 1435.92   816.7 1432.92   856.6 1432.79
#Mann= 3 , 0 , 0
       0      .1       0   420.4    .045       0   435.4      .1       0
Bank Sta=420.4,435.4
XS Rating Curve= 0 ,0
Exp/Cntr=0.3,0.1

Type RM Length L Ch R = 1 ,2008.9  ,170.5,169.6,168.7
XS GIS Cut Line= 4
     1782798.271       198523.65     1783108.364      198443.626
     1783325.096      198453.629     1783588.509      198413.617
#Sta/Elev= 30
       0  1590.7    24.6  1581.9    49.3  1568.1    59.1 1558.35    78.8 1534.91
    88.7 1526.42   128.1 1506.76   162.6 1486.48   231.6 1449.42   246.4 1436.51
     271 1410.74   275.9 1408.88   310.4 1407.88   344.9 1399.44   386.6 1393.94
   389.3 1393.91   401.6 1394.09   448.5 1396.01   487.9 1402.95   517.5 1414.35
   542.2  1414.8   547.1 1417.27   561.9 1430.28   586.6 1442.11   616.2  1448.9
   635.9 1456.74   650.7  1457.7   655.6 1459.86   724.7 1501.46   803.6 1544.21
#Mann= 3 , 0 , 0
       0      .1       0   386.6    .045       0   401.6      .1       0
Bank Sta=386.6,401.6
XS Rating Curve= 0 ,0
Exp/Cntr=0.3,0.1

Type RM Length L Ch R = 1 ,1839.3  ,297.4,302.2,307.3
XS GIS Cut Line= 4
     1782781.369      198609.878     1782994.997      198613.677
      1783458.47      198617.012     1783698.542      198510.313
#Sta/Elev= 30
       0 1558.86    49.7 1529.76    89.4 1515.55   114.3 1504.68   183.8 1466.46
   223.6 1441.59   253.5 1409.51   268.5 1405.84   353.2 1400.84   393.1 1387.85
   407.8  1384.5     413 1383.96   422.8 1384.79   437.9 1388.49   457.9 1388.91
   462.8 1390.54   502.7 1413.98   552.6 1415.18   557.5 1416.44   572.5 1425.97
   582.5 1430.09   612.4 1436.48   632.3 1451.15   652.2 1468.24   662.2 1470.01
   682.1 1482.28   746.5 1514.35   781.2 1527.83   830.8 1550.74   939.9 1609.56
#Mann= 3 , 0 , 0
       0      .1       0   407.8    .045       0   422.8      .1       0
Bank Sta=407.8,422.8
XS Rating Curve= 0 ,0
Exp/Cntr=0.3,0.1

Type RM Length L Ch R = 1 ,1537.1  ,264.6,260.4,255.9
XS GIS Cut Line= 4
     1782731.584      198760.388     1783011.669      198867.087
     1783356.141      198955.152     1783525.157      198940.442
#Sta/Elev= 30
       0    1597      25 1582.24      50 1571.72    59.9 1564.71    79.9 1554.77
   154.9 1511.07   184.8 1491.03   224.8 1456.69   274.7 1425.46   299.7 1414.21
   319.5 1402.33   339.2 1394.25   363.9 1391.17   378.7 1391.73   393.6 1386.82
   427.6 1379.59     438 1377.44   442.6 1377.83   536.8 1381.07   576.3 1380.06
   586.1 1382.12   620.7 1397.06   645.4 1402.57   670.2 1410.81   695.2 1422.92
   715.2 1436.04   740.1 1446.02     780 1467.83     810 1481.19   824.9 1485.67
#Mann= 3 , 0 , 0
       0      .1       0   427.6    .045       0   442.6      .1       0
#XS Ineff= 2 , 0
                          536.95         1381.04
Permanent Ineff=
       F       F
Bank Sta=427.6,442.6
XS Rating Curve= 0 ,0
Exp/Cntr=0.3,0.1

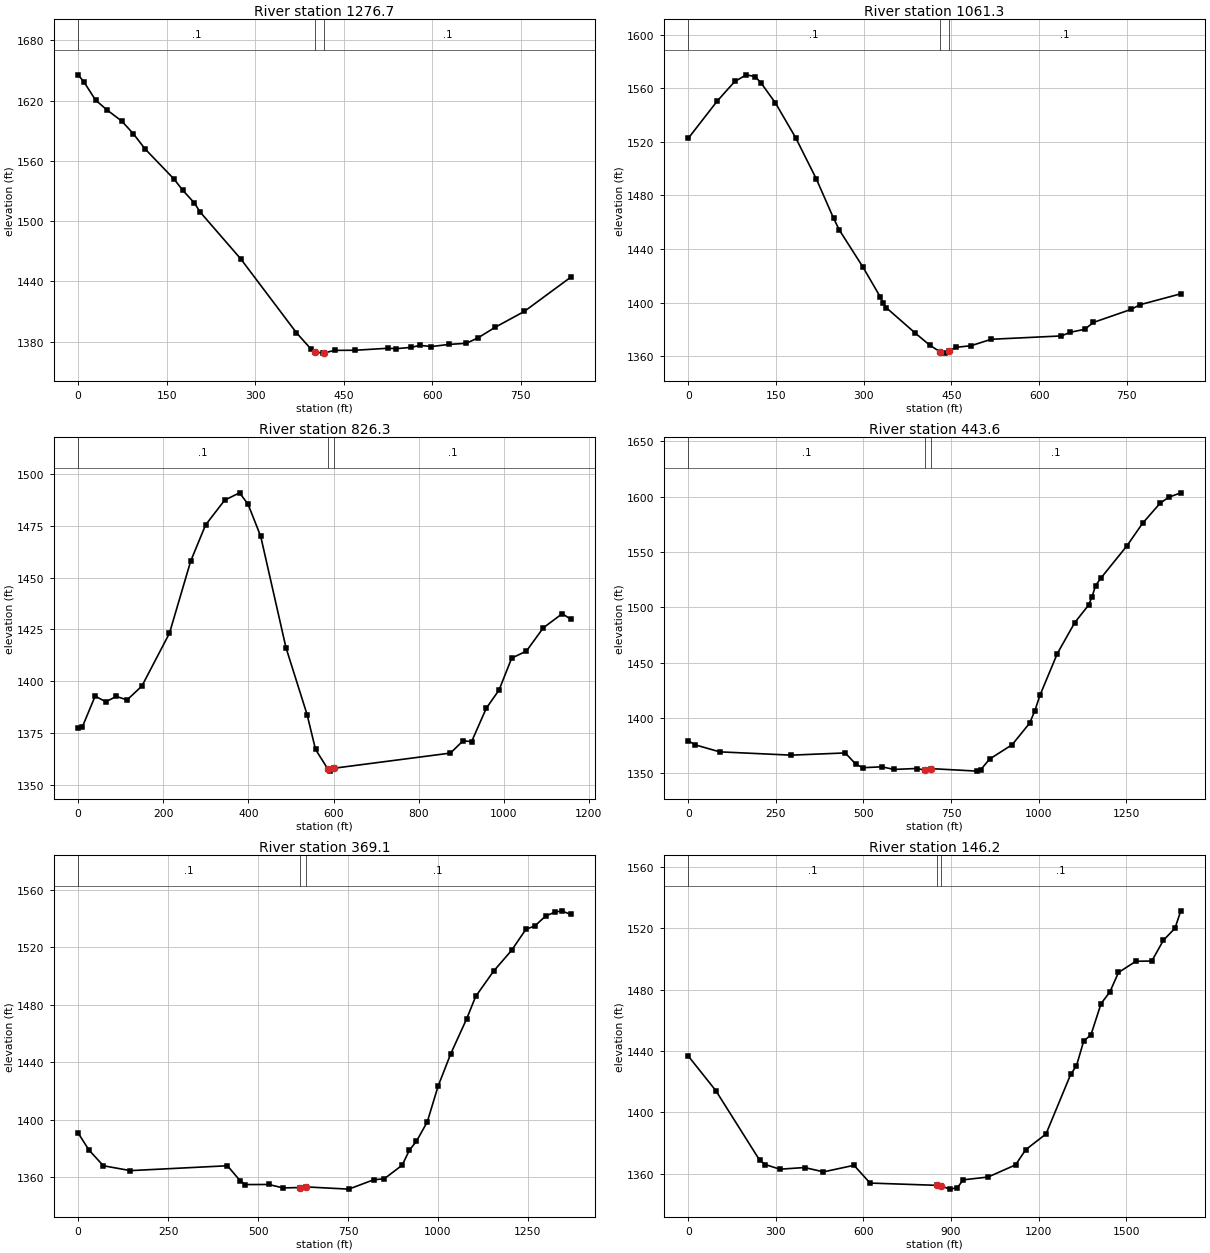
Type RM Length L Ch R = 1 ,1276.7  ,215.4,215.5,217.5
XS GIS Cut Line= 4
     1782684.904      199040.473     1782978.325      199123.831
     1783251.741      199137.168     1783499.846      199075.872
#Sta/Elev= 30
       0  1645.6     9.8 1638.49    29.5  1620.4    49.2 1610.48    73.8 1599.55
    93.5 1586.92   113.2 1571.92   162.4  1541.8   177.1 1530.72   196.8 1518.06
   206.6 1509.01   275.5 1462.29   369.7 1388.89   394.6 1372.43   401.9 1369.78
   414.5 1368.58   416.9 1368.81   434.4 1371.32   469.3 1371.44     524 1373.41
     539 1373.04   563.8 1374.29   578.8 1376.29   598.4 1375.12   627.9 1377.24
   657.4 1378.37   677.1 1383.72   706.6  1394.4   755.7 1410.11   834.3 1444.14
#Mann= 3 , 0 , 0
       0      .1       0   401.9    .045       0   416.9      .1       0
#XS Ineff= 2 , 0
                          524.58         1373.37
Permanent Ineff=
       F       F
Bank Sta=401.9,416.9
XS Rating Curve= 0 ,0
Exp/Cntr=0.3,0.1

Type RM Length L Ch R = 1 ,1061.3  ,232.3,234.9,235.6
XS GIS Cut Line= 4
     1782671.001      199336.441     1782968.322      199310.554
     1783268.413      199363.903     1783488.479      199270.542
#Sta/Elev= 30
       0 1522.52    49.7 1550.43    79.6    1565    99.5 1569.94   114.4 1568.59
   124.4 1563.94   149.2 1548.89     184 1522.76   218.9 1492.39   248.7 1462.73
   258.6 1453.98   298.4 1426.74   328.4 1404.22   333.4  1399.4   338.4 1396.24
   388.4 1377.14   413.4 1368.07   430.4 1363.33   438.4 1362.26   445.4 1363.85
   458.3 1366.63   483.3 1367.76   518.3  1372.6   638.1 1375.09     653 1377.78
     678 1380.06   692.9 1385.17   757.6 1394.96   772.6 1398.39   842.3 1406.53
#Mann= 3 , 0 , 0
       0      .1       0   430.4    .045       0   445.4      .1       0
Bank Sta=430.4,445.4
XS Rating Curve= 0 ,0
Exp/Cntr=0.3,0.1

Type RM Length L Ch R = 1 ,826.3   ,386,382.8,379.9
XS GIS Cut Line= 4
     1782448.166      199563.964     1782844.952      199520.617
     1783231.735      199580.635     1783561.834      199420.587
#Sta/Elev= 30
       0 1377.29      10 1377.96    39.9 1392.76    64.9 1390.03    89.8 1392.62
   114.8  1390.9   149.7  1397.6   214.5 1423.16   264.4 1458.04   299.4 1475.54
   344.3 1487.51   379.2 1491.06   399.2 1485.55   428.9 1470.04   488.3 1416.19
   537.9 1383.82   557.7 1366.98   587.3 1357.32   592.4 1356.48   602.3 1357.91
   874.8 1365.21   904.6 1371.17   924.4 1370.71   959.1 1386.93   988.9 1395.66
  1018.6 1411.11  1053.3 1414.54    1093 1425.78  1137.6 1432.63  1157.4  1429.9
#Mann= 3 , 0 , 0
       0      .1       0   587.3    .045       0   602.3      .1       0
Bank Sta=587.3,602.3
XS Rating Curve= 0 ,0
Exp/Cntr=0.3,0.1

Type RM Length L Ch R = 1 ,443.6   ,69,74.5,119.4
XS GIS Cut Line= 4
     1782478.174      199663.994     1782904.555      199869.091
      1783405.12      199890.729     1783825.247      199790.699
#Sta/Elev= 30
       0 1379.28    19.9  1375.7    89.6 1369.35   293.8 1366.37   448.2 1368.36
   478.1  1358.3     498 1355.02   552.5 1355.83   587.2 1353.47   651.7  1354.3
   676.9 1352.84   691.9 1354.21   825.4 1351.93   835.3 1353.32   860.1 1362.78
   924.6  1375.8   974.2 1395.13   989.1  1406.2    1004 1420.47  1053.6 1458.18
  1103.2 1486.07    1143 1502.04  1152.9 1509.71  1162.8 1519.55  1177.7 1526.26
  1252.2 1555.46  1296.8 1575.83  1346.5 1593.84  1371.3 1599.39    1406  1603.4
#Mann= 3 , 0 , 0
       0      .1       0   676.9    .045       0   691.9      .1       0
Bank Sta=676.9,691.9
XS Rating Curve= 0 ,0
Exp/Cntr=0.3,0.1

Type RM Length L Ch R = 1 ,369.1   ,172,222.9,84.4
XS GIS Cut Line= 4
     1782490.293       199717.49     1783013.511      199916.568
     1783304.472      199993.137     1783812.377      199970.167
#Sta/Elev= 30
       0 1390.85      30 1379.04      70 1368.15     145 1364.75   414.9 1368.14
   449.8 1357.85   464.8 1355.07   529.8 1355.13   569.7 1352.73     617 1353.01
     632 1353.46   752.2  1351.9   821.2 1358.38   850.8 1359.11   900.6 1368.51
   920.5 1378.89   940.4 1385.21   970.3 1398.57  1000.2 1423.24  1035.1 1445.63
    1080 1470.29  1104.9 1485.74  1154.8 1503.35  1204.6 1517.72  1244.5  1532.4
  1269.4 1534.75  1299.3 1541.58  1324.2 1544.24  1344.2 1545.23  1369.1 1542.68
#Mann= 3 , 0 , 0
       0      .1       0     617    .045       0     632      .1       0
Bank Sta=617,632
XS Rating Curve= 0 ,0
Exp/Cntr=0.3,0.1

Type RM Length L Ch R = 1 ,146.2   ,57.1,56.9,52.3
XS GIS Cut Line= 4
     1782341.467      199660.659     1783020.173      199984.436
     1783308.638      200095.888     1783931.946      200047.443
#Sta/Elev= 30
       0  1436.8    94.6 1414.15     244    1369   263.9    1366   313.7 1362.98
   398.4 1364.07   463.1 1361.24   567.7 1365.52   622.5 1353.94   851.6 1352.46
   866.6  1351.9   896.6 1349.99   921.6 1350.96   941.5 1356.06  1026.3 1357.86
  1120.8 1365.81  1155.5 1375.71    1225 1385.95  1309.3 1424.75  1329.2 1430.38
    1354 1446.53  1378.8 1450.56  1413.5 1470.97  1443.3 1478.45  1473.1 1491.22
  1532.6 1498.53  1587.2 1498.69  1626.9 1512.23  1666.6  1520.1  1686.4 1531.42
#Mann= 3 , 0 , 0
       0      .1       0   851.6    .045       0   866.6      .1       0
Bank Sta=851.6,866.6
XS Rating Curve= 0 ,0
Exp/Cntr=0.3,0.1

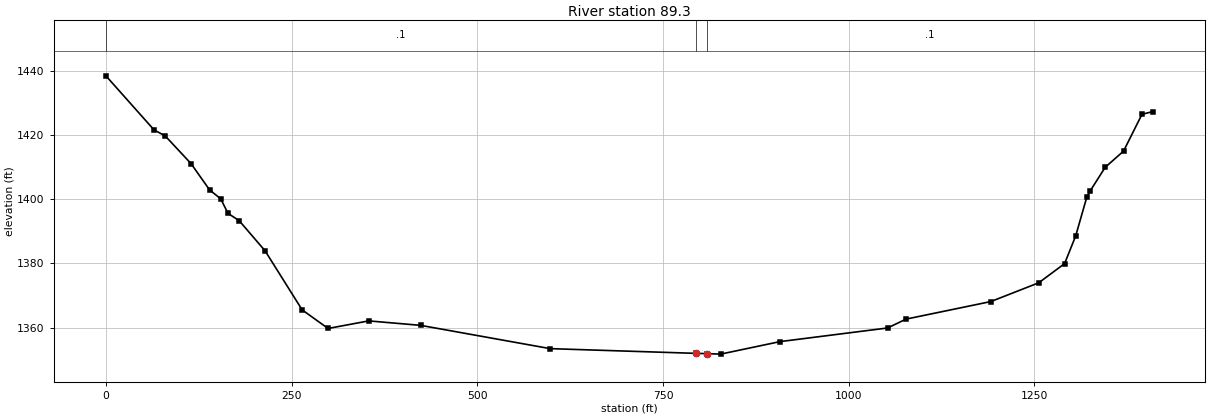
Type RM Length L Ch R = 1 ,89.3    ,87.1,89.3,94.3
XS GIS Cut Line= 4
     1782360.199      199700.341     1782980.837      200019.401
     1783339.233      200143.966     1783671.406      200159.263
#Sta/Elev= 30
       0 1438.47    64.8 1421.61    79.8 1419.74   114.6 1411.11   139.6  1402.9
   154.5 1400.14   164.5 1395.57   179.4 1393.32   214.3 1383.91   264.2  1365.5
   299.1  1359.7   353.9 1362.06   423.7 1360.67   598.2 1353.41   794.4 1351.94
   809.4 1351.85   827.6  1351.7   907.5  1355.6  1052.3 1359.85  1077.3 1362.62
  1191.4 1368.09  1255.9 1373.94  1290.7 1379.92  1305.6 1388.53  1320.5 1400.58
  1325.4 1402.67  1345.3 1409.93  1370.1 1415.01  1394.9 1426.48  1409.8 1427.34
#Mann= 3 , 0 , 0
       0      .1       0   794.4    .045       0   809.4      .1       0
Bank Sta=794.4,809.4
XS Rating Curve= 0 ,0
Exp/Cntr=0.3,0.1

Chan Stop Cuts=-1
Use User Specified Reach Order=0